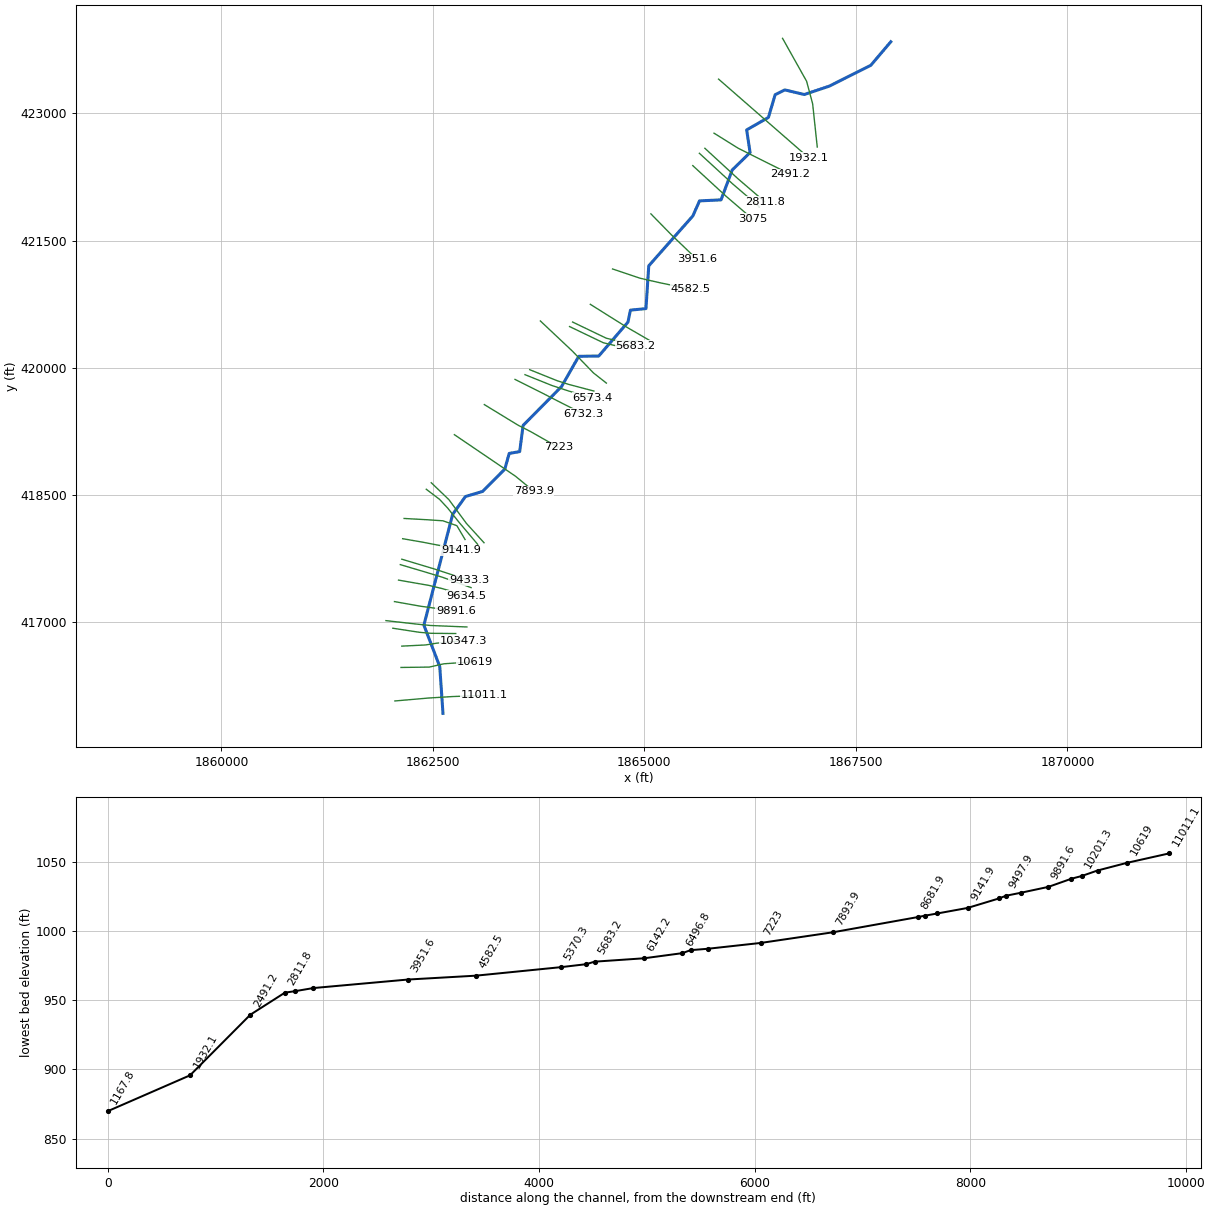
--- WhitesRun.prj (project) ---

Proj Title=WhitesRun
Current Plan=p01
Default Exp/Contr=0,0
English Units
Geom File=g01
Flow File=f01
Plan File=p01
BEGIN DESCRIPTION:
END DESCRIPTION:
DSS Export Rating Curves= 0
DSS Export Rating Curve Sorted= 0
DSS Export Volume Flow Curves= 0
DXF OffsetX= 0
DXF OffsetY= 0
DXF ScaleX= 0
DXF ScaleY= 0

--- WhitesRun.p01 (plan) ---

Plan Title=Floodplain
Program Version=4.00
Geom File=g01
Flow File=f01
K Sum by GR=0
Std Step Tol=0.01
Critical Tol=0.01
Num of Std Step Trials=20
Max Error Tol=0.3
Flow Tol Ratio=0.001
Split Flow NTrial=30
Split Flow Tol=0.02
Split Flow Ratio=0.02
Log Output Level=0
Friction Slope Method=1
Unsteady Friction Slope Method=2
Unsteady Bridges Friction Slope Method=1
Global Log Level=0
CheckData=False
Run HTab=0
Run UNet=0
Run PostProcess=0
UNET Theta=0
UNET Theta Warmup=0
UNET ZTol=0
UNET ZSATol=0
UNET MxIter=0
UNET MaxInSteps=0
UNET DtIC=0
UNET DtMin=0
UNET MaxCRTS=0
UNET WFStab=0
UNET SFStab=0
UNET WFX=0
UNET SFX=0
UNET DSS MLevel=0
UNET DZMax Abort=0
UNET Convert EG Bridges=0
UNET Use Existing IB Tables=0
UNET Froude Limit=0
UNET Froude Power=0
Write IC File=0
Echo Input=False
Echo Output=False
Write Detailed=0

--- WhitesRun.f01 (steady flow) ---

Flow Title=NFF Regression Equation
Program Version=4.10
Number of Profiles= 1
Profile Names=P100yr
River Rch & RM=WhitesRun,Main            ,11011.1
     237
River Rch & RM=WhitesRun,Main            ,9141.9
     302
River Rch & RM=WhitesRun,Main            ,8750.1
     398
River Rch & RM=WhitesRun,Main            ,6732.3
     435
River Rch & RM=WhitesRun,Main            ,6142.2
     517
River Rch & RM=WhitesRun,Main            ,5683.2
     541
River Rch & RM=WhitesRun,Main            ,1167.8
     686
Boundary for River Rch & Prof#=WhitesRun,Main            , 1
Up Type= 0
Dn Type= 3
Dn Slope=0.03395
DSS Import GetInterval= 0
DSS Import GetPeak= 0
DSS Import FillOption= 0

--- WhitesRun.g01 (geometry) ---

Geom Title=USGS 10m DEM
Program Version=4.10

River Reach=WhitesRun       ,Main
Reach XY= 30
     1862619.146       415928.98     1862581.024      416481.136
     1862393.334      416968.253     1862733.585      418273.493
     1862884.626      418483.563     1863086.883      418543.459
     1863349.904       418806.48     1863401.987      418991.375
     1863526.119      419013.077      1863566.05      419321.237
     1864020.911       419779.57     1864224.036      420135.473
     1864460.736      420139.261     1864806.097      420538.835
     1864835.171      420679.734     1865018.564      420697.626
     1865051.664      421201.731     1865573.214      421789.928
     1865651.491      421966.611     1865906.002      421978.772
     1866037.946      422330.335     1866249.412      422536.286
     1866208.867      422802.731     1866466.505        422950.3
     1866545.498      423217.661     1866659.995      423274.432
     1866889.367      423219.814     1867184.639      423318.237
     1867676.759      423564.298     1867912.558       423841.14

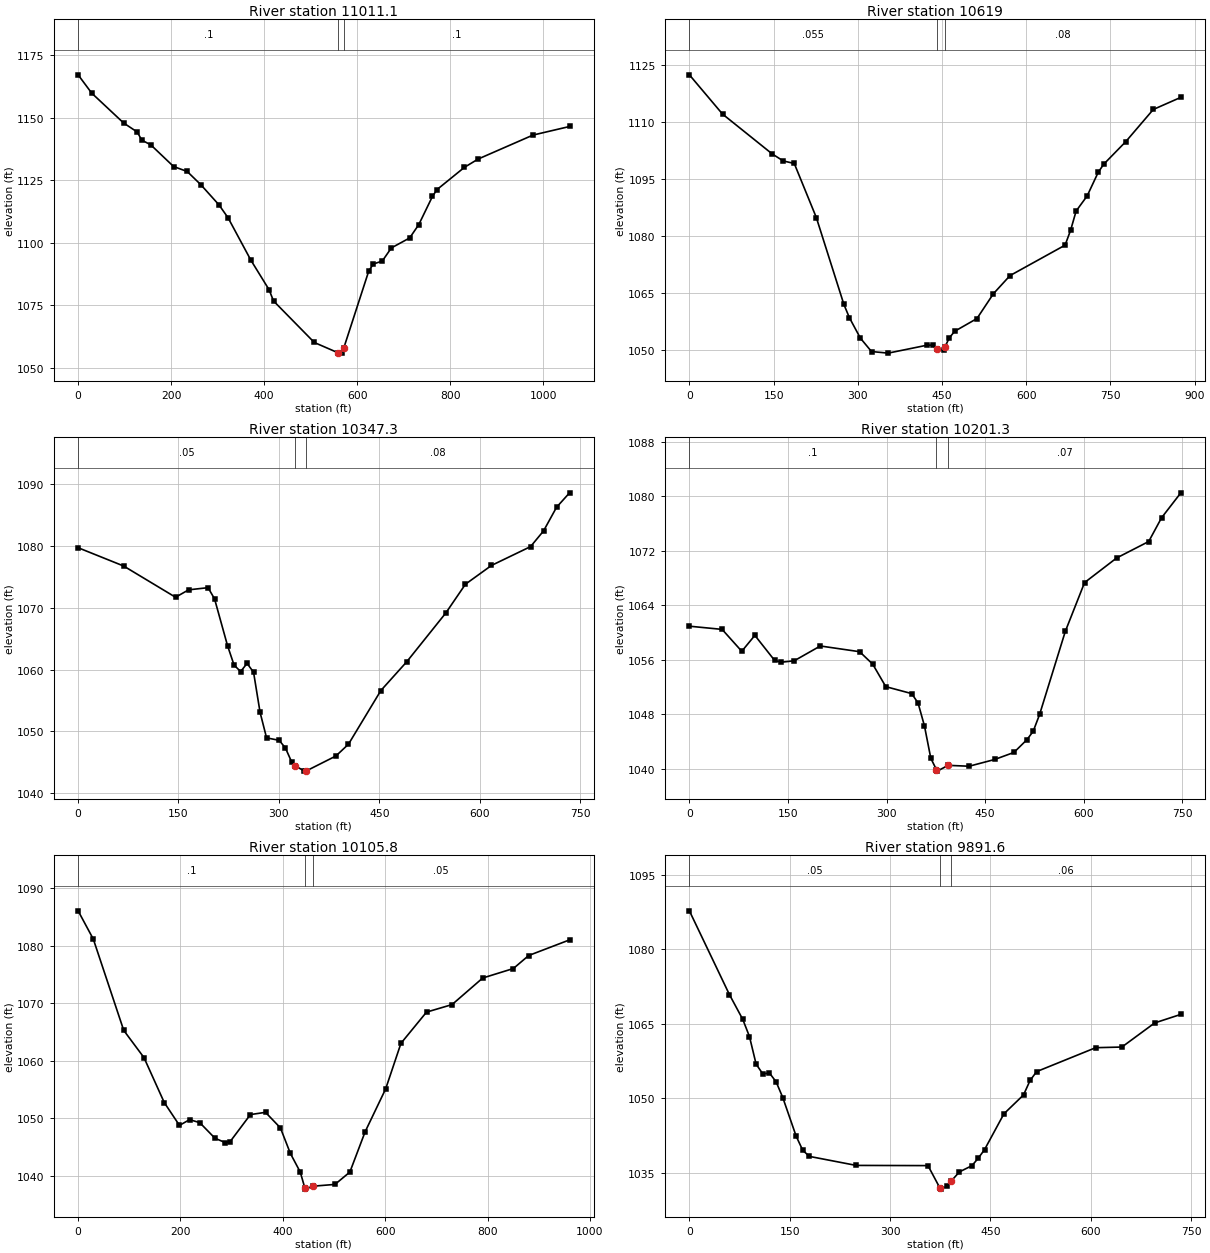
Type RM Length L Ch R = 1 ,11011.1 ,389.3,392.1,396.3
XS GIS Cut Line= 4
     1862050.787      416075.161     1862450.092      416109.883
      1862732.21      416127.244     1863105.474      416140.265
#Sta/Elev= 30
       0 1167.11    29.3 1159.79    97.8 1147.88   127.1 1144.27   136.9 1141.03
   156.4 1139.12   205.3 1130.48   234.6  1128.5     264  1123.2     303 1115.15
   322.6 1109.97   371.5 1093.08   410.6  1081.3   420.3 1076.77     508 1060.18
   559.9    1056   566.5 1055.93  571.43 1058.01     625 1088.67   634.7 1091.51
   654.2 1092.72   673.7 1097.96     713 1101.93   732.6 1107.24   762.1 1118.54
   771.9 1121.27   830.9 1130.16   860.4 1133.47   978.3 1143.04    1057 1146.47
#Mann= 3 , 0 , 0
       0      .1       0   559.9    .045       0  571.43      .1       0
Bank Sta=559.9,571.43
XS Rating Curve= 0 ,0
Exp/Cntr=0.3,0.1

Type RM Length L Ch R = 1 ,10619   ,271.6,271.7,269.5
XS GIS Cut Line= 4
     1862123.125      416469.945     1862457.326      416474.286
     1862630.937      416513.348      1862993.35       416537.22
#Sta/Elev= 30
       0  1122.5      59 1112.15   147.4 1101.65   167.1 1099.79   186.8 1099.12
   226.1 1084.86   275.2 1061.94   285.1 1058.41   304.7 1053.02   324.4 1049.51
     354 1049.09   423.2 1051.18   433.1 1051.18   440.6 1050.13   452.9 1049.99
  454.98 1050.65   462.8 1053.08   472.6 1054.86   512.2 1058.21   541.6 1064.77
   571.1 1069.54   669.2 1077.57   679.1 1081.53   688.9 1086.58   708.5 1090.55
   728.1 1096.75     738 1098.92   777.2 1104.86   826.3 1113.36   875.4 1116.56
#Mann= 3 , 0 , 0
       0    .055       0   440.6    .045       0  454.98     .08       0
#XS Ineff= 2 , 0
          433.07 1051.18
Permanent Ineff=
       F       F
Bank Sta=440.6,454.98
XS Rating Curve= 0 ,0
Exp/Cntr=0.3,0.1

Type RM Length L Ch R = 1 ,10347.3 ,151.5,146,141
XS GIS Cut Line= 4
     1862132.239      416721.247     1862413.489      416735.136
     1862543.698       416755.97     1862863.142       416787.22
#Sta/Elev= 30
       0 1079.76      68  1076.8   145.6 1071.74   165.1 1072.94   194.2 1073.29
   203.9 1071.47   223.3 1063.89     233 1060.77   242.8  1059.7   252.5 1061.03
   262.2 1059.58   271.9  1053.1   281.6 1048.97   300.4 1048.57   309.8 1047.33
   319.3 1045.01   323.8 1044.49   338.1 1043.58  341.08 1043.62   385.2 1046.03
     404 1047.94   452.4 1056.63   491.3 1061.32   549.6 1069.21   578.8 1073.85
   617.7 1076.89   676.1 1079.94   695.5 1082.48     715 1086.32   734.4 1088.65
#Mann= 3 , 0 , 0
       0     .05       0   323.8    .045       0  341.08     .08       0
Bank Sta=323.8,341.08
XS Rating Curve= 0 ,0
Exp/Cntr=0.3,0.1

Type RM Length L Ch R = 1 ,10201.3 ,95.6,95.5,95.3
XS GIS Cut Line= 4
     1862026.365      416932.163      1862341.47      416883.986
     1862476.886      416872.267     1862769.855      416869.663
#Sta/Elev= 30
       0 1060.93    49.8 1060.46    79.7 1057.24    99.6 1059.58   129.5 1055.92
   139.5 1055.63   159.4 1055.84   199.2 1058.02     259 1057.18   278.9 1055.35
   298.8 1052.04   338.2 1051.02   347.9 1049.64   357.6 1046.28   367.3 1041.51
  375.77 1039.85     377 1039.62   393.8 1040.47   425.6 1040.34   464.4 1041.33
   493.8 1042.37   513.3 1044.22     523 1045.46   532.8 1047.95   571.9 1060.16
   601.2 1067.34     650 1070.96   698.8 1073.38   718.4 1076.88   747.7 1080.54
#Mann= 3 , 0 , 0
       0      .1       0  375.77    .045       0   393.8     .07       0
Bank Sta=375.77,393.8
XS Rating Curve= 0 ,0
Exp/Cntr=0.3,0.1

Type RM Length L Ch R = 1 ,10105.8 ,214.5,214.2,213.6
XS GIS Cut Line= 4
     1861945.173      417021.595      1862299.34      416981.664
     1862472.951      416964.303      1862901.77      416946.942
#Sta/Elev= 30
       0 1086.04    29.7 1081.12    89.1 1065.26   128.7 1060.52   168.3 1052.71
     198 1048.74   217.8 1049.74   237.6 1049.22   267.3 1046.51   287.1 1045.76
     297 1045.92   336.6 1050.62   366.1 1051.01   395.2 1048.31   414.6 1043.88
     434 1040.62  442.96 1037.85   443.6 1037.66   458.9 1038.17   501.8 1038.48
   530.9 1040.63   560.8 1047.65   600.8 1055.08   630.7 1063.01   680.6 1068.43
   730.5 1069.74   790.4 1074.36   850.3 1076.01   880.2 1078.27   960.1 1080.99
#Mann= 3 , 0 , 0
       0      .1       0  442.96    .045       0   458.9     .05       0
Bank Sta=442.96,458.9
XS Rating Curve= 0 ,0
Exp/Cntr=0.3,0.1

Type RM Length L Ch R = 1 ,9891.6  ,259.7,257.1,254.5
XS GIS Cut Line= 4
     1862045.795      417245.965     1862360.031       417190.41
      1862490.24      417173.049      1862771.49      417133.118
#Sta/Elev= 30
       0 1087.73    59.8 1070.89    79.8 1065.89    89.8 1062.44    99.7  1056.9
   109.7 1054.93   119.7  1055.1   129.6 1053.34   139.6 1050.16   159.6 1042.39
   169.5 1039.54   179.5 1038.33   249.3 1036.52   356.6 1036.48  374.51 1031.95
   375.4 1031.75   384.8 1032.29   390.8  1033.3   403.6 1035.22   422.3 1036.47
   431.7 1037.97   441.1 1039.69   470.1  1046.9   499.4  1050.7   509.2 1053.62
     519 1055.39   607.2  1060.2   646.4 1060.33   695.4 1065.18   734.5  1066.9
#Mann= 3 , 0 , 0
       0     .05       0  374.51    .045       0   390.8     .06       0
Bank Sta=374.51,390.8
XS Rating Curve= 0 ,0
Exp/Cntr=0.3,0.1

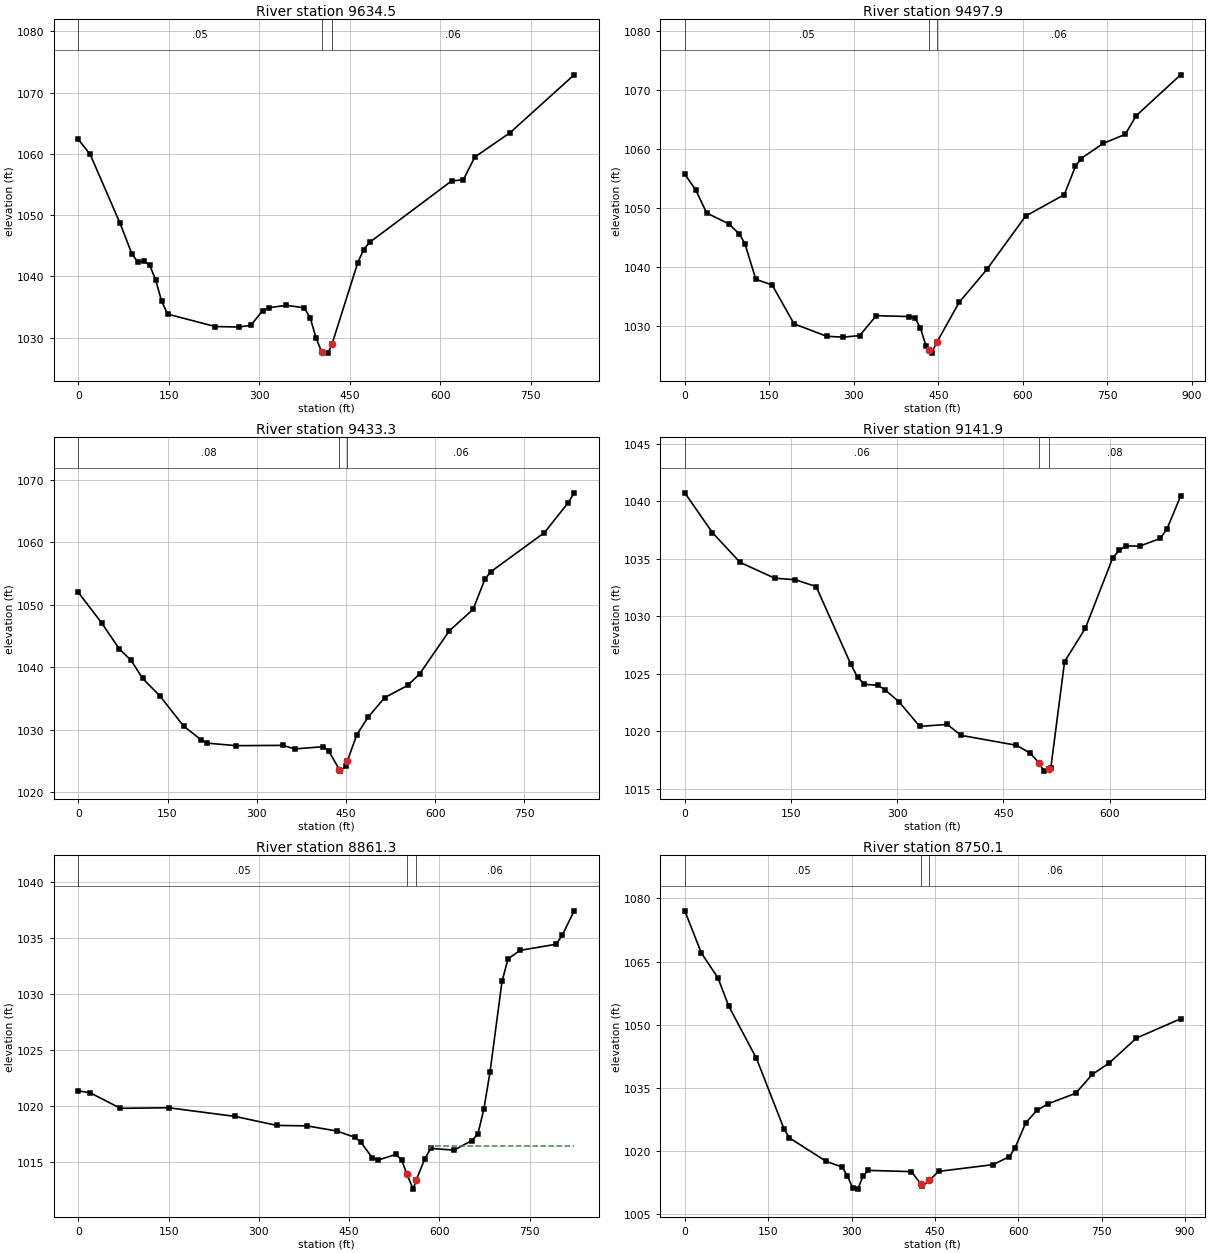
Type RM Length L Ch R = 1 ,9634.5  ,137.8,136.6,135.2
XS GIS Cut Line= 4
     1862094.045      417499.025      1862453.42      417436.525
     1862606.198      417400.067     1862894.392      417316.733
#Sta/Elev= 30
       0 1062.35    19.7 1059.89      69  1048.7    88.7  1043.7    98.6 1042.34
   108.4 1042.48   118.3 1041.83   128.2 1039.39     138 1035.98   147.9 1033.85
   226.8 1031.82   266.2 1031.74   285.9 1032.02   305.6 1034.43   315.5 1034.89
     345 1035.28   374.6 1034.88   384.4 1033.21   394.2  1029.9  403.55 1027.63
   413.8 1027.48   420.4 1028.93   462.9 1042.17   472.8 1044.36   482.6 1045.54
   618.6 1055.57     638 1055.77   657.3 1059.49   715.4 1063.43   821.8 1072.89
#Mann= 3 , 0 , 0
       0     .05       0  403.55    .045       0   420.4     .06       0
Bank Sta=403.55,420.4
XS Rating Curve= 0 ,0
Exp/Cntr=0.3,0.1

Type RM Length L Ch R = 1 ,9497.9  ,65.1,64.6,64.1
XS GIS Cut Line= 4
     1862114.878      417681.317     1862403.073      417596.247
      1862609.67      417533.747     1862951.684      417410.483
#Sta/Elev= 30
       0 1055.67    19.4 1053.01    38.8 1049.09    77.6 1047.28    96.9 1045.54
   106.6 1043.91     126 1037.86   155.1 1036.89   193.9  1030.3     252 1028.19
   281.1 1028.05   310.3 1028.31   339.7 1031.69   398.6 1031.54   408.4 1031.32
   418.2 1029.57     428 1026.59   433.5 1025.89   437.8 1025.34   447.6 1027.23
   486.9 1033.95     536 1039.52   604.8 1048.57   673.5 1052.21   693.2    1057
     703 1058.32   742.3 1060.88   781.6 1062.43   801.3 1065.62   879.9 1072.52
#Mann= 3 , 0 , 0
       0     .05       0   433.5    .045       0   447.6     .06       0
Bank Sta=433.5,447.6
XS Rating Curve= 0 ,0
Exp/Cntr=0.3,0.1

Type RM Length L Ch R = 1 ,9433.3  ,288.3,291.4,294
XS GIS Cut Line= 4
     1862132.239      417745.553     1862508.975      417632.706
     1862642.656      417589.303     1862927.378      417495.553
#Sta/Elev= 30
       0 1051.99    39.3 1047.09    68.8 1042.94    88.5 1041.14   108.2 1038.22
   137.6 1035.38     177  1030.6   206.5 1028.41   216.3 1027.88   265.5 1027.47
   344.1 1027.52   363.8 1026.95     412 1027.31   421.4 1026.56   438.9 1023.63
   440.1  1023.4   449.5 1024.19  452.13 1024.98   468.2 1029.22     487 1032.01
   515.1 1035.16   553.8 1037.11   573.8 1038.95   623.8 1045.85   663.7 1049.28
   683.7 1054.13   693.7 1055.31   783.6 1061.54   823.6 1066.33   833.6 1067.91
#Mann= 3 , 0 , 0
       0     .08       0   438.9    .045       0  452.13     .06       0
Bank Sta=438.9,452.13
XS Rating Curve= 0 ,0
Exp/Cntr=0.3,0.1

Type RM Length L Ch R = 1 ,9141.9  ,284.2,280.6,277.3
XS GIS Cut Line= 4
     1862142.656      417986.872     1862373.559      417946.942
     1862708.628      417882.706     1862829.534      417851.217
#Sta/Elev= 30
       0 1040.73      39 1037.27    78.1 1034.68   126.9 1033.31   156.2 1033.17
   185.5 1032.58   234.3 1025.86   244.1 1024.69   253.8 1024.08   273.3 1023.99
   283.1 1023.58   302.6 1022.56   331.8 1020.42   370.8 1020.59   390.3 1019.64
   468.3 1018.78   487.8  1018.1   500.1 1017.26   507.3 1016.53   515.1 1016.74
     517 1016.79   536.5 1026.06   565.8 1028.95   604.3 1035.04   613.9 1035.76
   623.6 1036.11   642.8  1036.1   671.6 1036.76   681.2  1037.6   700.4 1040.45
#Mann= 3 , 0 , 0
       0     .06       0   500.1    .045       0   515.1     .08       0
Bank Sta=500.1,515.1
XS Rating Curve= 0 ,0
Exp/Cntr=0.3,0.1

Type RM Length L Ch R = 1 ,8861.3  ,123.8,111.2,97.7
XS GIS Cut Line= 5
     1862159.829      418225.349     1862439.343      418209.724
     1862618.379      418197.788      1862783.31      418140.279
     1862880.315      417977.085
#Sta/Elev= 30
       0 1021.34      20 1021.15      70 1019.77     150 1019.82     260 1019.05
   329.8 1018.24   379.6  1018.2   429.5 1017.74   459.4 1017.18   469.1 1016.76
   488.5 1015.34   498.2 1015.14   527.3 1015.64     537 1015.19   546.2 1013.85
   556.4 1012.54   561.2 1013.32   575.8 1015.26   585.5 1016.18   624.4 1016.03
     654 1016.89     664 1017.48     674 1019.75     684 1022.98     704 1031.12
     714 1033.14     734  1033.9   793.9 1034.45   803.9 1035.24   823.9 1037.44
#Mann= 3 , 0 , 0
       0     .05       0   546.2    .045       0   561.2     .06       0
#XS Ineff= 2 , 0
                          585.12         1016.39
Permanent Ineff=
       F       F
Bank Sta=546.2,561.2
XS Rating Curve= 0 ,0
Exp/Cntr=0.3,0.1

Type RM Length L Ch R = 1 ,8750.1  ,69,68.2,68.3
XS GIS Cut Line= 5
     1862421.548      418569.533     1862579.534      418449.741
     1862675.888      418346.443     1862810.002      418178.908
     1863028.752      417921.095
#Sta/Elev= 30
       0 1077.05    29.7 1067.06    59.5 1061.17    79.3 1054.37   128.9 1042.04
   178.4 1025.33   188.4 1023.14   254.8 1017.56     283 1016.24   292.4 1014.22
   301.9 1011.32   311.3    1011   320.7 1014.13   330.1 1015.45   407.8 1015.15
   424.9 1012.19   427.3 1011.64   439.9 1013.05   456.6 1015.21   554.1  1016.8
     584 1018.69   593.9  1020.7   613.8 1026.81   633.7 1029.68   653.6 1031.25
   703.3 1033.74   733.1 1038.21     763 1040.86   812.7 1046.85   892.2 1051.42
#Mann= 3 , 0 , 0
       0     .05       0   424.9    .045       0   439.9     .06       0
#XS Ineff= 2 , 0
          388.49 1015.21
Permanent Ineff=
       F       F
Bank Sta=424.9,439.9
XS Rating Curve= 0 ,0
Exp/Cntr=0.3,0.1

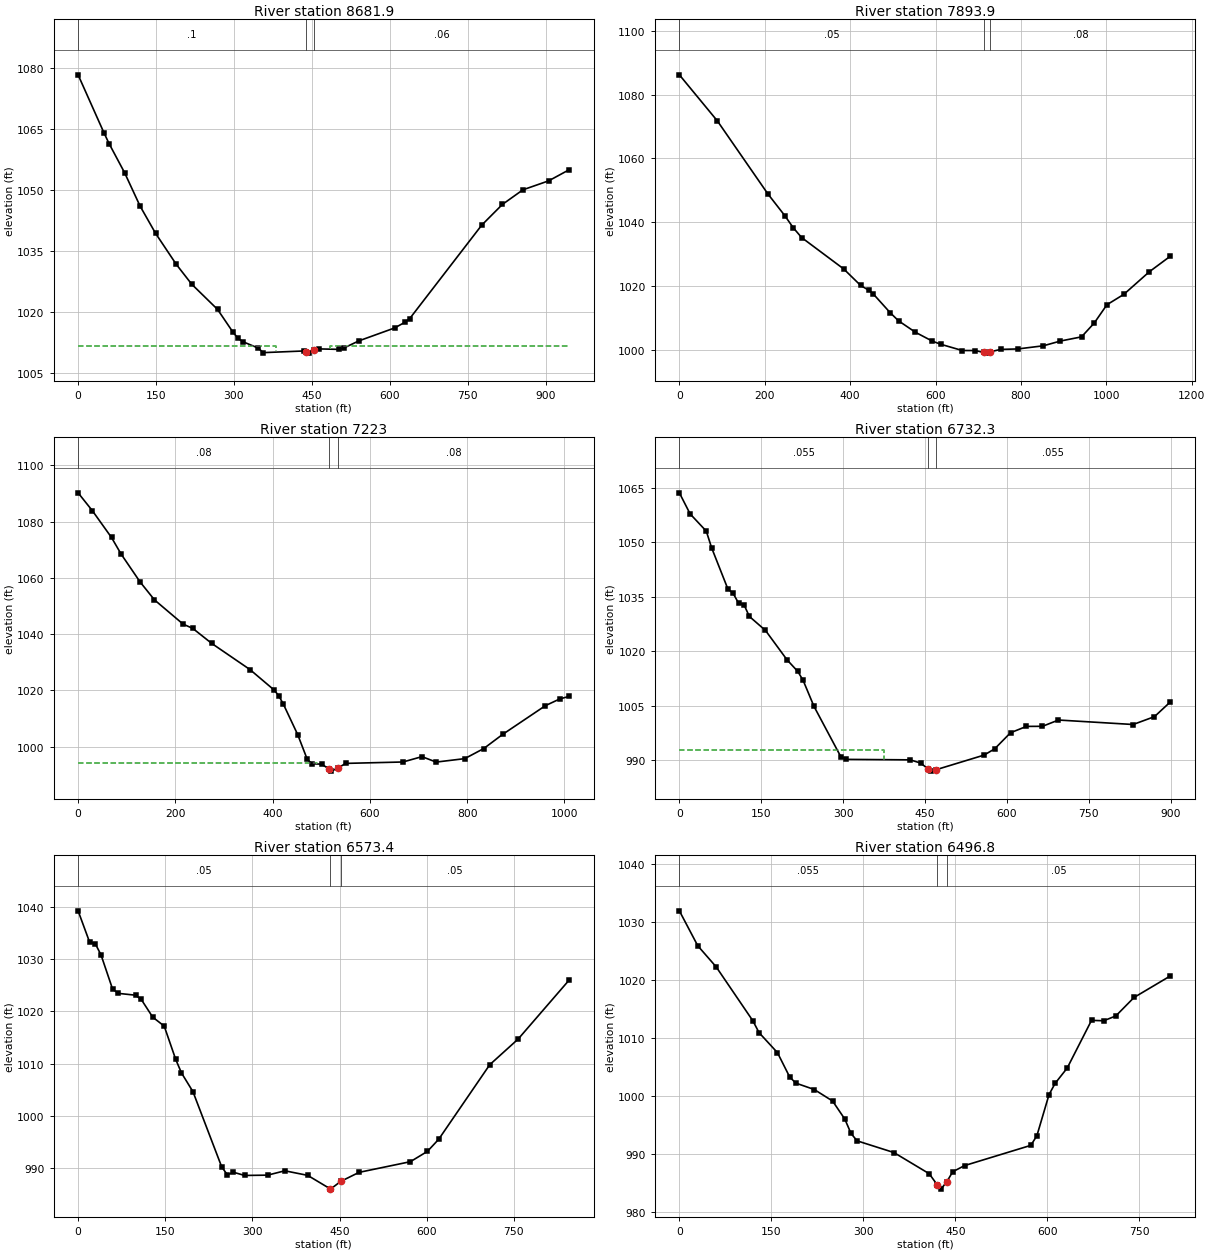
Type RM Length L Ch R = 1 ,8681.9  ,780.3,788,795.3
XS GIS Cut Line= 4
     1862480.575      418646.356     1862688.909      418447.137
     1862897.242      418165.887     1863104.273      417939.325
#Sta/Elev= 30
       0 1078.33    49.7 1064.11    59.6 1061.44    89.5 1054.28   119.3 1046.08
   149.1 1039.39   188.9 1031.78   218.7 1026.89   268.4  1020.7     298 1015.12
   307.7 1013.62   317.4 1012.75   346.6 1011.21   356.3 1010.08   434.1 1010.49
   438.4 1010.26   443.8 1009.96   453.4 1010.75   463.3    1011   502.2 1010.88
   511.9 1011.25     541    1013   609.1 1016.14   628.5  1017.5   638.3 1018.45
   776.9 1041.41   816.5 1046.48   856.1 1050.08   905.6 1052.28   945.2 1055.02
#Mann= 3 , 0 , 0
       0      .1       0   438.4    .045       0   453.4     .06       0
#XS Ineff= 2 , 0
          380.11 1011.75  484.37         1011.72
Permanent Ineff=
       F       F
Bank Sta=438.4,453.4
XS Rating Curve= 0 ,0
Exp/Cntr=0.3,0.1

Type RM Length L Ch R = 1 ,7893.9  ,669.6,670.9,671.7
XS GIS Cut Line= 4
     1862753.767      419212.567     1863236.406      418886.178
     1863475.989      418722.983     1863691.267      418547.636
#Sta/Elev= 30
       0 1086.21    88.9 1071.78   207.4 1048.86   246.9 1042.07   266.6 1038.29
   286.4 1035.19   385.1 1025.33   424.6 1020.17   444.4 1018.62   454.3 1017.49
   493.8 1011.63   513.5 1009.07     553 1005.49   592.6 1002.71   612.6 1001.72
   662.6  999.78   692.6  999.77   713.7  999.16   722.6  998.96   728.7  999.39
   752.6 1000.13   792.6 1000.27   852.5 1001.26   892.4 1002.75   941.9 1004.06
   971.7  1008.4  1001.4 1014.13  1041.1  1017.4  1100.6 1024.46  1150.2 1029.38
#Mann= 3 , 0 , 0
       0     .05       0   713.7    .045       0   728.7     .08       0
Bank Sta=713.7,728.7
XS Rating Curve= 0 ,0
Exp/Cntr=0.3,0.1

Type RM Length L Ch R = 1 ,7223    ,489.6,490.7,491.3
XS GIS Cut Line= 4
     1863107.934      419566.733     1863510.711      419321.942
     1863651.336      419250.761     1863982.934      419063.261
#Sta/Elev= 30
       0 1090.25    29.5 1083.85    68.7 1074.36    88.4 1068.48   127.6 1058.52
   157.1 1052.16     216 1043.53   235.7 1042.04   274.9 1036.67   353.5 1027.37
   402.6 1020.18   412.4 1018.14   422.2 1015.05   451.7  1004.2   471.3   995.4
   481.2  993.86   500.9  993.73  516.08  992.01   520.6  991.25   534.5  992.35
   550.1     994     668   994.5   707.1   996.4   736.4  994.47     795  995.69
   834.1  999.27   873.1 1004.32     961 1014.54   990.4 1016.92  1009.9 1017.85
#Mann= 3 , 0 , 0
       0     .08       0  516.08    .045       0   534.5     .08       0
#XS Ineff= 2 , 0
          491.09  994.01  560.66          994.02
Permanent Ineff=
       F       F
Bank Sta=516.08,534.5
XS Rating Curve= 0 ,0
Exp/Cntr=0.3,0.1

Type RM Length L Ch R = 1 ,6732.3  ,154.4,158.9,162.7
XS GIS Cut Line= 4
     1863470.781      419863.608      1863797.17      419700.414
     1864021.128      419585.831       1864274.6      419459.095
#Sta/Elev= 30
       0 1063.56    19.7 1057.77    49.3 1053.03    59.2 1048.41    88.8 1037.16
    98.6  1035.9   108.5 1033.22   118.4 1032.81   128.2 1029.58   157.8 1025.72
   197.2 1017.66     217 1014.45   226.8 1011.99   246.6 1004.87   295.9  990.98
   305.7  990.27     423  990.14   442.3  989.25   455.2   987.7   461.7  987.04
   470.2  987.42   558.4  991.45   577.8  993.17   606.8  997.59     636  999.34
   665.3  999.36   694.7 1001.09   831.5  999.86   870.6 1002.02   899.9  1006.1
#Mann= 3 , 0 , 0
       0    .055       0   455.2    .045       0   470.2    .055       0
#XS Ineff= 2 , 0
          374.63  992.93
Permanent Ineff=
       F       F
Bank Sta=455.2,470.2
XS Rating Curve= 0 ,0
Exp/Cntr=0.3,0.1

Type RM Length L Ch R = 1 ,6573.4  ,77.4,76.5,76.2
XS GIS Cut Line= 4
     1863588.836      419919.164     1863910.017      419790.692
     1864106.198      419726.456     1864387.448      419644.858
#Sta/Elev= 30
       0 1039.19    19.8 1033.21    29.6 1032.91    39.5 1030.76    59.3 1024.26
    69.2 1023.43    98.8 1023.08   108.7 1022.27   128.5 1018.88   148.2 1017.18
     168 1010.82   177.9 1008.24   197.7 1004.65   247.1  990.31     257  988.76
   266.8  989.29   286.6  988.66   326.2  988.72   355.8  989.55   395.1  988.68
  433.69  986.12   434.4  986.05   451.9  987.52   483.5  989.25   571.9  991.29
   601.2  993.26   620.7  995.58   708.5 1009.81   757.3  1014.7   845.2 1025.98
#Mann= 3 , 0 , 0
       0     .05       0  433.69    .045       0   451.9     .05       0
#XS Ineff= 2 , 0
          355.63  989.51
Permanent Ineff=
       F       F
Bank Sta=433.69,451.9
XS Rating Curve= 0 ,0
Exp/Cntr=0.3,0.1

Type RM Length L Ch R = 1 ,6496.8  ,365.6,354.6,343.4
XS GIS Cut Line= 4
     1863644.392      419978.192     1863969.045      419847.983
     1864106.198      419804.581     1864403.073      419726.456
#Sta/Elev= 30
       0  1031.9      30 1025.87      60 1022.23   119.9 1012.91   129.9 1010.88
   159.9 1007.43   179.9 1003.22   189.9 1002.17   219.9 1001.07   249.8  999.08
   269.8  995.95   279.8  993.49   289.8  992.21   349.8  990.19   407.3  986.54
   420.6  984.59   426.5  983.88   436.1  985.18   445.7  986.88   464.9  987.94
   572.9  991.43   582.8  993.08   602.6 1000.18   612.5 1002.12   632.3 1004.78
   671.9    1013   691.7 1012.93   711.5 1013.76   741.2 1016.95   800.6 1020.68
#Mann= 3 , 0 , 0
       0    .055       0   420.6    .045       0   436.1     .05       0
Bank Sta=420.6,436.1
XS Rating Curve= 0 ,0
Exp/Cntr=0.3,0.1

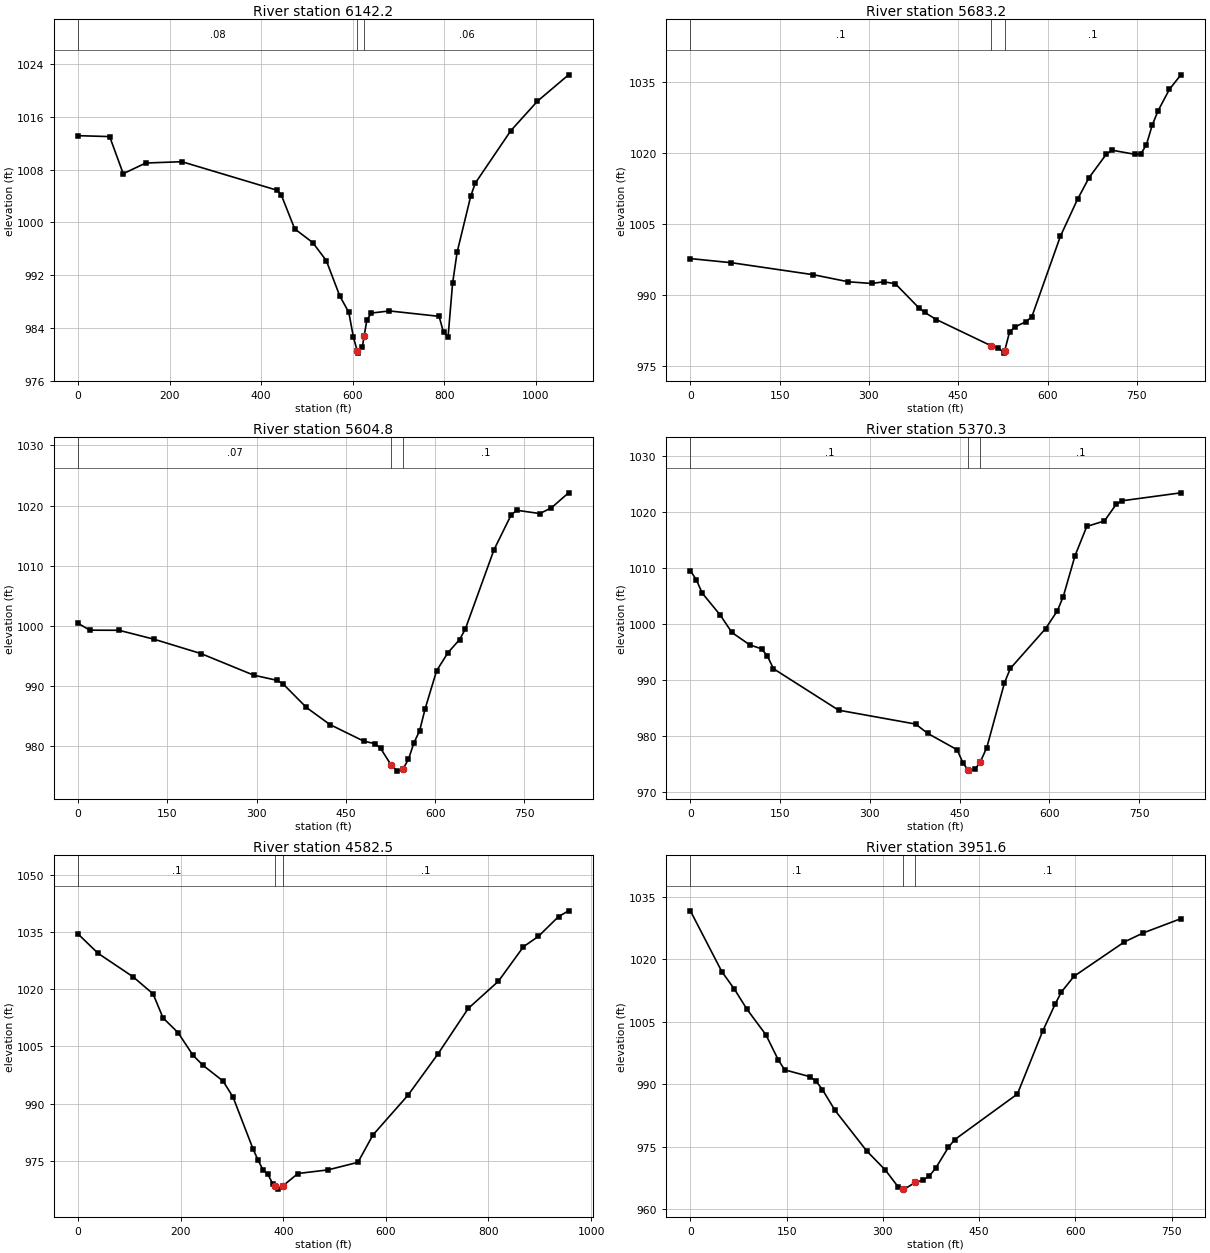
Type RM Length L Ch R = 1 ,6142.2  ,438.1,459,478.2
XS GIS Cut Line= 4
      1863770.26      420552.324     1864150.989      420194.685
     1864397.864      419939.997     1864550.642      419820.206
#Sta/Elev= 30
       0 1013.17      69 1013.03    98.6  1007.4   147.8 1009.02   226.7 1009.22
   433.7 1004.91   443.5 1004.23   473.1  999.03   512.5  996.95   542.1  994.22
   571.6  988.84   591.3  986.36   601.2  982.63   609.7   980.5     611  980.18
   620.9  981.17   624.7  982.73   630.7   985.2   640.6  986.26     680  986.58
   788.4  985.76   798.2  983.31   808.1  982.69   817.9  990.78   827.8  995.49
   857.4 1003.96   867.2 1005.94     945 1013.92  1003.2  1018.4  1071.2  1022.4
#Mann= 3 , 0 , 0
       0     .08       0   609.7    .045       0   624.7     .06       0
#XS Ineff= 2 , 0
                          672.94           986.5
Permanent Ineff=
       F       F
Bank Sta=609.7,624.7
XS Rating Curve= 0 ,0
Exp/Cntr=0.3,0.1

Type RM Length L Ch R = 1 ,5683.2  ,84.2,78.4,70.6
XS GIS Cut Line= 4
     1864115.558        420486.2     1864514.864      420295.227
     1864651.582      420262.675     1864892.468       420259.42
#Sta/Elev= 30
       0  997.72    68.8  996.85   206.6  994.31   265.6  992.81   304.9  992.46
   324.6  992.81   344.3  992.41   383.6  987.34   393.4  986.36   413.1  984.84
   505.5  979.27   517.6  978.91     527  977.73  528.11  978.23   536.3  982.24
   545.7   983.3   564.4  984.41   573.8  985.46   621.7 1002.46   650.6  1010.3
   669.9 1014.85   698.8 1019.79   708.4 1020.64     747 1019.77   756.6 1019.82
   766.2 1021.82   775.9 1025.91   785.5 1028.91   804.8 1033.51   824.1 1036.58
#Mann= 3 , 0 , 0
       0      .1       0   505.5    .045       0  528.11      .1       0
Bank Sta=505.5,528.11
XS Rating Curve= 0 ,0
Exp/Cntr=0.3,0.1

Type RM Length L Ch R = 1 ,5604.8  ,241.5,234.4,225.8
XS GIS Cut Line= 4
     1864151.365      420539.368     1864550.671      420348.396
      1864687.39      420315.844     1864928.275      420312.589
#Sta/Elev= 30
       0 1000.45    19.7  999.31    68.8  999.29   127.9   997.8   206.6  995.42
   295.1  991.84   334.4  990.98   344.3   990.4   383.6  986.48     423  983.65
   480.1  980.88   498.8  980.47   508.2   979.7   525.9  976.94   536.3  975.91
   545.7  976.24   555.1  977.88   564.4  980.64   573.8   982.6   583.2   986.3
   602.4  992.58   621.7   995.6     641  997.75   650.6  999.49   698.8 1012.66
   727.7 1018.46   737.3 1019.21   775.9 1018.67   795.2 1019.62   824.1 1022.11
#Mann= 3 , 0 , 0
       0     .07       0   525.9    .045       0   545.7      .1       0
Bank Sta=525.9,545.7
XS Rating Curve= 0 ,0
Exp/Cntr=0.3,0.1

Type RM Length L Ch R = 1 ,5370.3  ,780.5,787.9,795.2
XS GIS Cut Line= 3
     1864361.059       420748.07     1864789.535      420479.955
     1865062.013      420322.723
#Sta/Elev= 30
       0 1009.54     9.9 1007.93    19.8 1005.54    49.6 1001.66    69.4  998.51
    99.1  996.31   118.9  995.59   128.8   994.3   138.8  992.05   247.8  984.64
   376.6  982.16   396.4  980.52     446  977.57   455.9  975.16  464.86  973.89
   465.8  973.76   475.7  974.09   484.3  975.33   495.5  977.96   525.1  989.53
   534.9  992.09   593.9  999.21   613.6  1002.4   623.4 1004.93   643.1 1012.24
   662.7 1017.44   692.2 1018.42   711.9  1021.4   721.7 1022.02     820 1023.44
#Mann= 3 , 0 , 0
       0      .1       0  464.86    .045       0   484.3      .1       0
Bank Sta=464.86,484.3
XS Rating Curve= 0 ,0
Exp/Cntr=0.3,0.1

Type RM Length L Ch R = 1 ,4582.5  ,643.4,630.8,619
XS GIS Cut Line= 4
     1864623.645      421164.737     1864946.996       421056.23
     1865174.861      421004.147     1865548.125      420926.022
#Sta/Elev= 30
       0 1034.44      39 1029.38   107.2 1023.23   146.2 1018.76   165.7 1012.45
   194.9 1008.61   224.1 1002.67   243.6 1000.04   282.6  995.93   302.1  991.72
   341.1  978.13   350.8  975.23   360.6  972.65   370.3  971.47     380  968.84
   383.6  968.39   389.8  967.62   398.6   968.4   428.7  971.71   487.2  972.66
   545.6  974.64   574.8   981.8   643.3  992.24   701.9 1003.09   760.6 1014.94
   819.3 1022.05   868.2  1031.1   897.5 1033.84   936.6 1038.99   956.2 1040.51
#Mann= 3 , 0 , 0
       0      .1       0   383.6    .045       0   398.6      .1       0
Bank Sta=383.6,398.6
XS Rating Curve= 0 ,0
Exp/Cntr=0.3,0.1

Type RM Length L Ch R = 1 ,3951.6  ,873.9,876.7,877.3
XS GIS Cut Line= 3
     1865077.204      421813.608     1865317.482      421568.715
     1865621.909      421277.584
#Sta/Elev= 30
       0  1031.6      49 1017.01    68.6 1012.81    88.2 1007.97   117.6 1001.88
   137.2  995.76     147  993.44   186.2  991.81     196  990.69   205.8  988.68
   225.4  983.71   274.5  974.03   303.9  969.38   323.5  965.41  331.35  964.91
   333.3  964.82   350.6  966.44   362.7     967   372.5  968.01   382.3  969.87
   401.9  974.82   411.6  976.67   509.6  987.65   548.8 1002.68   568.4 1009.22
   578.2 1012.14   597.8  1015.9   676.2 1024.13   705.5 1026.29   764.3 1029.72
#Mann= 3 , 0 , 0
       0      .1       0  331.35    .045       0   350.6      .1       0
Bank Sta=331.35,350.6
XS Rating Curve= 0 ,0
Exp/Cntr=0.3,0.1

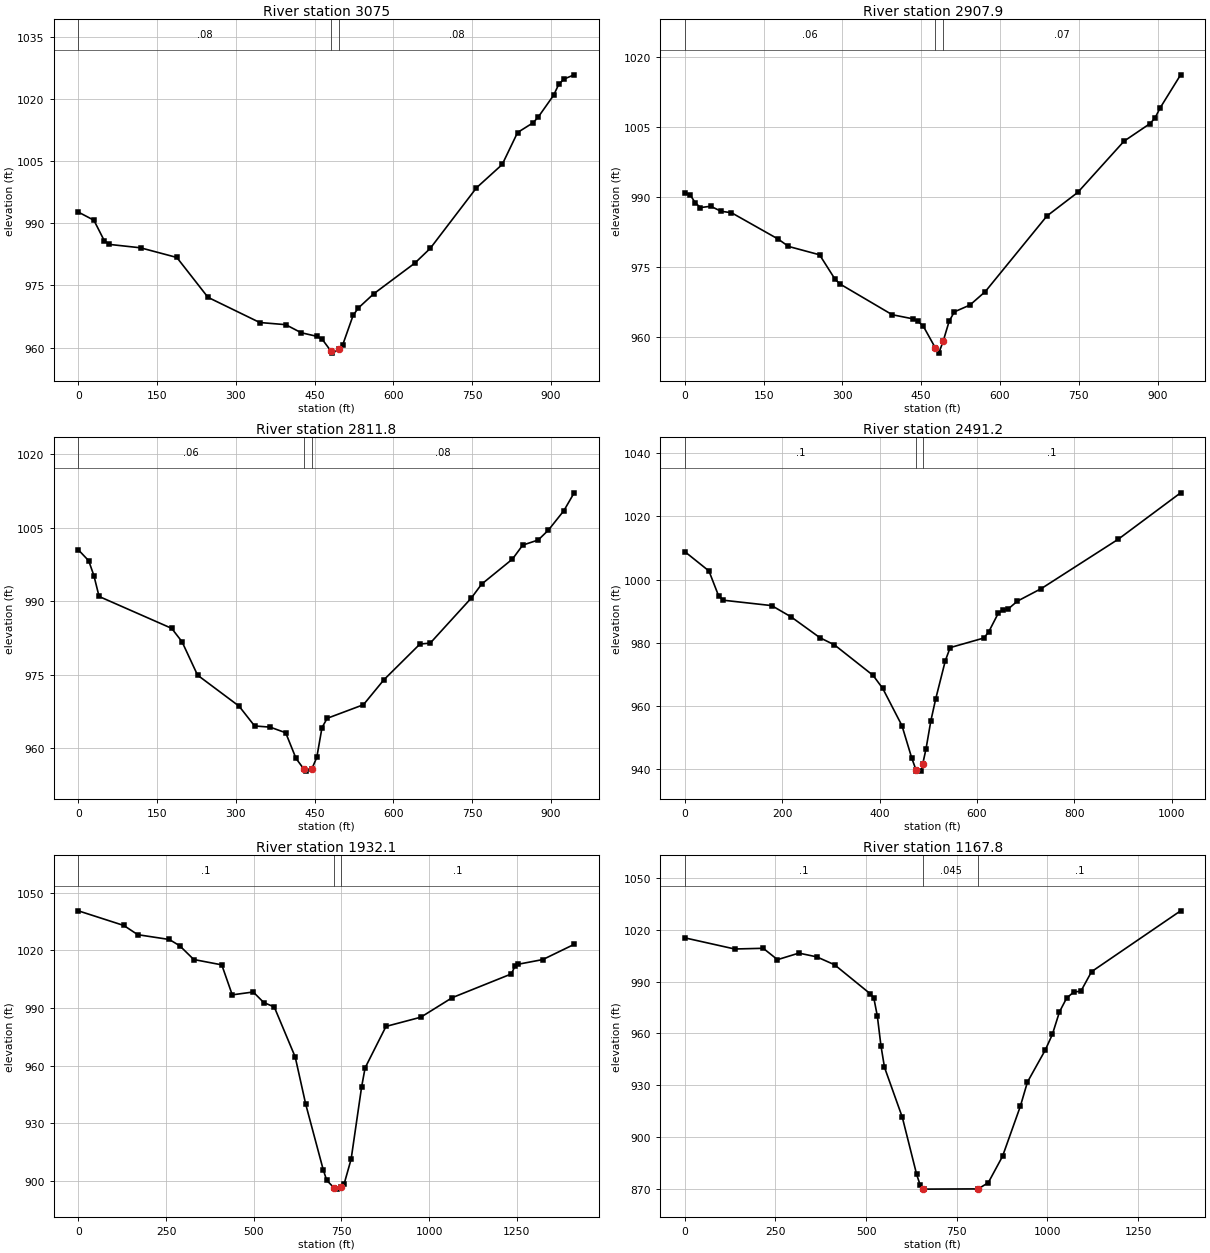
Type RM Length L Ch R = 1 ,3075    ,165.7,167.1,168.4
XS GIS Cut Line= 3
     1865571.996      422382.185     1865964.791      422021.942
     1866277.291      421755.015
#Sta/Elev= 30
       0  992.71    29.6  990.75    49.4  985.81    59.2  984.91   118.4  984.09
   187.5  981.76   246.8  972.14   345.4  966.06   394.8  965.54   424.4  963.59
     454  962.73   463.9  962.08   481.5  959.07   483.6  958.67   496.5  959.62
   503.4  960.68   523.1  967.76     533  969.55   562.3  972.98   640.6  980.39
     670  983.95     758  998.57     807  1004.2   836.3 1011.92   865.7 1014.26
   875.5 1015.63   904.8 1020.89   914.6 1023.52   924.4 1024.81     944 1025.84
#Mann= 3 , 0 , 0
       0     .08       0   481.5    .045       0   496.5     .08       0
Bank Sta=481.5,496.5
XS Rating Curve= 0 ,0
Exp/Cntr=0.3,0.1

Type RM Length L Ch R = 1 ,2907.9  ,99.5,96.2,93.8
XS GIS Cut Line= 3
     1865650.121      422527.584     1866042.916      422167.341
     1866355.416      421900.414
#Sta/Elev= 30
       0  990.85     9.9  990.46    19.7  988.78    29.6   987.7    49.4  987.98
    69.1   986.9    88.8   986.6   177.7  980.94   197.4  979.36   256.6  977.56
   286.2  972.29   296.1  971.25   394.8   964.7   434.3  963.81   444.2  963.25
     454  962.25   476.9  957.59   483.6  956.45   491.9  959.01   503.4  963.32
   513.2  965.31   542.8  966.77   572.1  969.66   689.5   985.9   748.2  990.96
   836.3 1001.96   885.2 1005.69     895 1006.88   904.8 1009.06     944  1016.2
#Mann= 3 , 0 , 0
       0     .06       0   476.9    .045       0   491.9     .07       0
Bank Sta=476.9,491.9
XS Rating Curve= 0 ,0
Exp/Cntr=0.3,0.1

Type RM Length L Ch R = 1 ,2811.8  ,311.4,320.6,328.6
XS GIS Cut Line= 3
     1865715.225      422586.178      1866108.02      422225.935
      1866420.52      421959.008
#Sta/Elev= 30
       0 1000.48    19.7  998.26    29.6  995.23    39.5  990.97   177.7  984.47
   197.4  981.74     227  974.93     306  968.61   335.6  964.57   365.2  964.33
   394.8  963.18   414.5  957.94   429.8  955.72   434.3  955.36   444.8  955.87
     454  958.16   463.9  964.23   473.8  966.13   542.8   968.9   581.9     974
   650.4  981.27     670  981.46   748.2  990.65   767.8  993.48   826.5  998.59
   846.1 1001.44   875.5 1002.48     895  1004.5   924.4 1008.46     944  1012.1
#Mann= 3 , 0 , 0
       0     .06       0   429.8    .045       0   444.8     .08       0
Bank Sta=429.8,444.8
XS Rating Curve= 0 ,0
Exp/Cntr=0.3,0.1

Type RM Length L Ch R = 1 ,2491.2  ,565.4,559.1,552.7
XS GIS Cut Line= 4
     1865823.732      422764.129     1866110.191      422586.178
     1866331.545      422475.501        1866720.      422282.358
#Sta/Elev= 30
       0 1008.88    49.6 1002.76    69.4   994.9    79.4   993.5   178.5   991.8
   218.2  988.25   277.7  981.63   307.5  979.36   386.7  969.73   406.5  965.62
   446.1   953.8   465.9   943.7   475.1  939.72   475.8  939.42   485.7  939.49
  488.92  941.79   495.6  946.55   505.5   955.4   515.4  962.28   535.2  974.39
   545.1  978.51   614.3  981.54   624.2  983.47   643.9  989.38   653.7  990.51
   663.6  990.65   683.3  993.22   732.6  997.21   890.4 1012.81  1018.5 1027.49
#Mann= 3 , 0 , 0
       0      .1       0   475.1    .045       0  488.92      .1       0
Bank Sta=475.1,488.92
XS Rating Curve= 0 ,0
Exp/Cntr=0.3,0.1

Type RM Length L Ch R = 1 ,1932.1  ,777.7,764.3,750.9
XS GIS Cut Line= 3
     1865876.587      423401.656     1866433.341      422917.243
     1866943.256      422474.202
#Sta/Elev= 30
       0 1040.67   129.6 1033.04   169.5 1028.23   259.3 1025.74   289.2 1022.44
   329.1  1015.3   408.9 1012.51   438.8  996.88   498.6  998.38   528.6  992.87
   558.5  990.59   618.3   964.5   648.2  939.92   698.1  905.79   708.1  900.24
     728  896.49     738  895.65   747.9  896.58   757.9  898.46   777.7  911.28
   807.5  948.83   817.5  958.82   877.1  980.44   976.4  985.24  1065.8  995.41
  1234.7 1007.81  1244.6 1011.82  1254.6 1012.86  1324.1 1015.27  1413.5  1023.2
#Mann= 3 , 0 , 0
       0      .1       0     728    .045       0   747.9      .1       0
Bank Sta=728,747.9
XS Rating Curve= 0 ,0
Exp/Cntr=0.3,0.1

Type RM Length L Ch R = 1 ,1167.8  ,1147.1,1167.8,1188.5
XS GIS Cut Line= 4
     1866633.194      423881.751     1866917.482      423376.108
     1866989.097      423109.181      1867043.35      422601.369
#Sta/Elev= 30
       0 1015.44   137.6 1008.97   216.3 1009.38   255.6 1002.79   314.6 1006.59
   363.8 1004.41   412.9  999.84   511.3     983   521.1  980.68   530.9  970.08
   540.8  952.97   550.6  940.36   599.8  911.35   639.3  878.24   649.2  871.92
  657.87  869.91     659   869.7  808.66  869.83   836.7  873.39   876.1  888.72
   925.2  917.71   944.8   931.8   993.9  950.33  1013.6  959.47  1033.2  972.55
  1052.9   980.5  1072.5  984.02  1092.2   984.5  1121.6  995.82  1367.2 1031.11
#Mann= 3 , 0 , 0
       0      .1       0  657.87    .045       0  808.66      .1       0
Bank Sta=657.87,808.66
XS Rating Curve= 0 ,0
Exp/Cntr=0.3,0.1

Chan Stop Cuts=-1
Use User Specified Reach Order=0
Composite Channel Slope=5